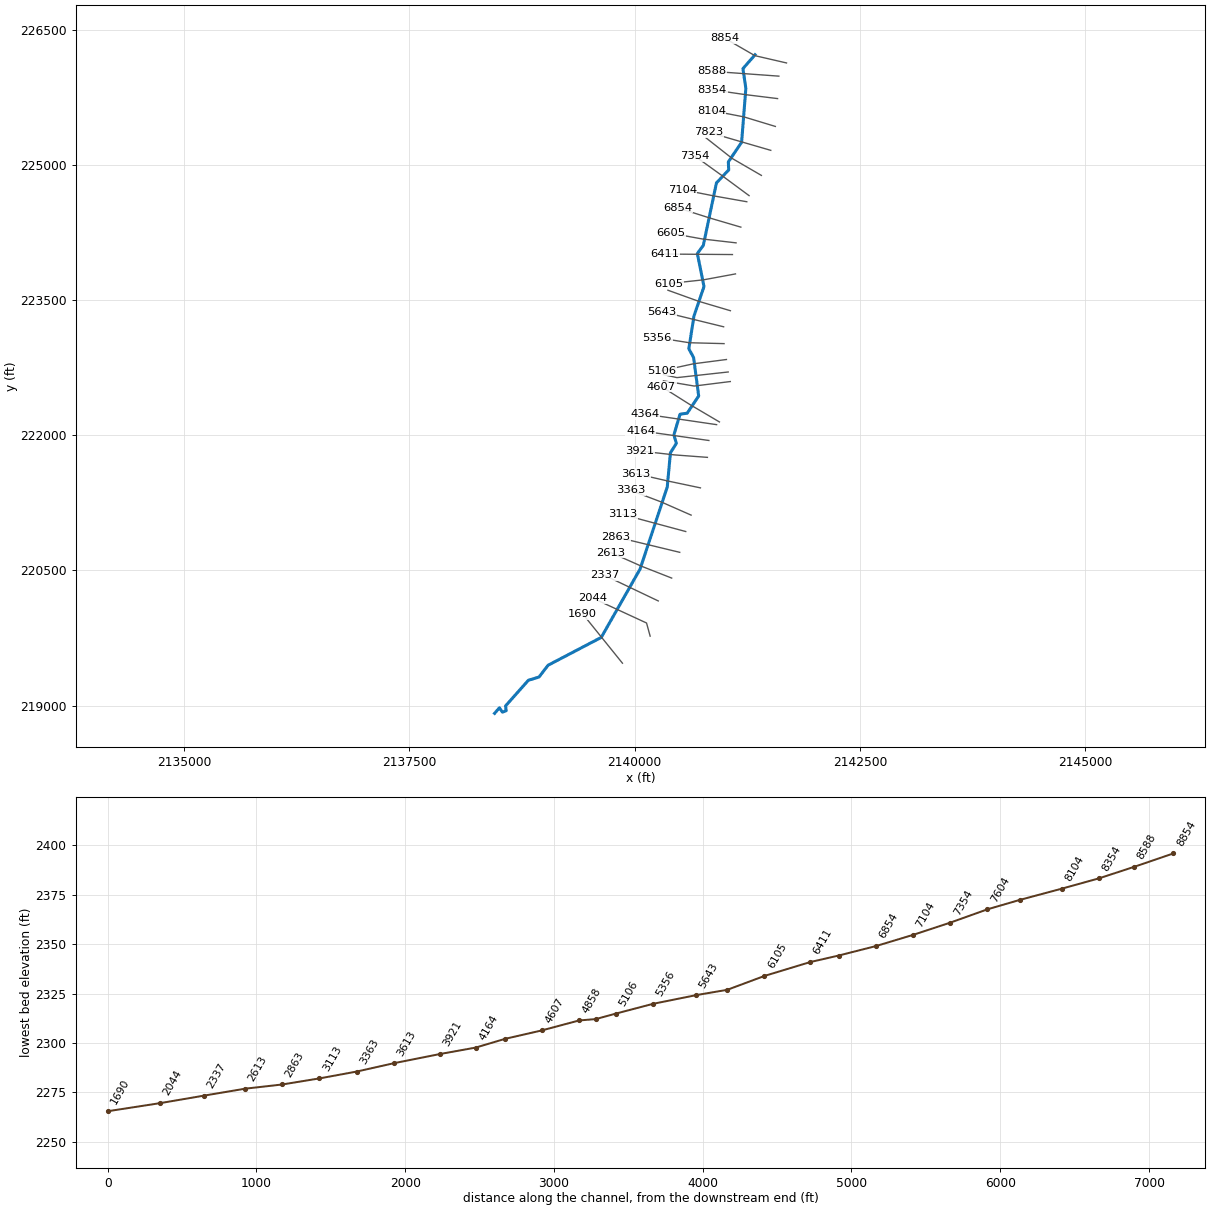
--- FORESTRN.prj (project) ---

Proj Title=FORESTRN
Current Plan=p01
Default Exp/Contr=0,0
English Units
Geom File=g01
Flow File=f01
Plan File=p01
Background Map Layer=Inundation Boundary (01pct Value_0)
BEGIN DESCRIPTION:
Stream Name: Forest Run
Flood Zone: Approximate
Monroe County, West Virginia
HEC-RAS Version: 5.0.7
Vertical Datum: NAVD88
Projection: NAD 1983 StatePlane West Virginia S FIPS 4702 (US Feet)
LiDAR: 2016, 1-meter
Land Use: 2016 NLCD
Hydrologic Method:
SIR2010-5033 regression equations
END DESCRIPTION:
DSS Export Rating Curves= 0
DSS Export Rating Curve Sorted= 0
DSS Export Volume Flow Curves= 0
DXF OffsetX= 0
DXF OffsetY= 0
DXF ScaleX= 0
DXF ScaleY= 0

--- FORESTRN.p01 (plan) ---

Plan Title=Floodplain
Program Version=5.07
Short Identifier=Floodplain
Geom File=g01
Flow File=f01
Subcritical Flow
K Sum by GR= 0
Std Step Tol= 0.01
Critical Tol= 0.01
Num of Std Step Trials= 20
Max Error Tol= 0.3
Flow Tol Ratio= 0.001
Split Flow NTrial= 30
Split Flow Tol= 0.02
Split Flow Ratio= 0.02
Log Output Level= 0
Friction Slope Method= 1
Unsteady Friction Slope Method= 2
Unsteady Bridges Friction Slope Method= 1
Parabolic Critical Depth
Global Vel Dist= 0 , 0 , 0
Global Log Level= 0
CheckData=True
Encroach Param=-1 ,0,0, 0
Mapping Interval=1HOUR
Computation Time Step Use Courant=        0
Computation Time Step Use Time Series=    0
Computation Time Step Count To Double=0
Computation Time Step Max Doubling=0
Computation Time Step Max Halving=0
Computation Time Step Residence Courant=0
Run HTab= 0
Run UNet= 0
Run Sediment= 0
Run PostProcess= 0
Run WQNet= 0
Run RASMapper=-1
UNET Theta= 0
UNET Theta Warmup= 0
UNET ZTol= 0
UNET ZSATol= 0
UNET MxIter= 0
UNET Max Iter WO Improvement= 0
UNET MaxInSteps= 0
UNET DtIC= 0
UNET DtMin= 0
UNET MaxCRTS= 0
UNET WFStab= 0
UNET SFStab= 0
UNET WFX= 1
UNET SFX= 1
UNET 1D Methodology=Finite Difference
UNET DSS MLevel= 1
UNET Pardiso=0
UNET DZMax Abort= 0
UNET Use Existing IB Tables= 0
UNET Froude Reduction=False
UNET Froude Limit= 0
UNET Froude Power= 0
UNET D1 Cores= 0
UNET D2 Coriolis=0
UNET D2 Cores= 0
UNET D2 Theta= 1
UNET D2 Theta Warmup= 1
UNET D2 Z Tol= 0.01
UNET D2 Volume Tol= 0.01
UNET D2 Max Iterations= 20
UNET D2 Equation= 0
UNET D2 RampUpFraction=0.1
UNET D2 TimeSlices= 1
UNET D2 BCVolumeCheck=0
UNET D1D2 MaxIter= 0
UNET D1D2 ZTol=0.01
UNET D1D2 QTol=0.1
UNET D1D2 MinQTol=1
Write IC File= 0
Write IC File at Fixed DateTime=0
Write IC File at Sim End=0
Echo Input=False
Echo Parameters=False
Echo Output=False
Write Detailed= 0
HDF Write Warmup=0
HDF Write Time Slices=0
HDF Flush=0
HDF Face Node Velocities=0
HDF Compression= 1
HDF Chunk Size= 1
HDF Spatial Parts= 1
HDF Use Max Rows=0
HDF Fixed Rows= 1
Calibration Method= 0
Calibration Iterations= 20
Calibration Max Change=0.05
Calibration Tolerance=0.2
Calibration Maximum=1.5
Calibration Minimum=0.5
Calibration Optimization Method= 1
WQ AD Non Conservative
WQ ULTIMATE=-1
WQ Max Comp Step=1HOUR
WQ Output Interval=15MIN
WQ Output Selected Increments= 0
WQ Output face flow=0
WQ Output face velocity=0
WQ Output face area=0
WQ Output face dispersion=0
WQ Output cell volume=0
WQ Output cell surface area=0
WQ Output cell continuity=0
WQ Output cumulative cell continuity=0
WQ Output face conc=0
WQ Output face dconc_dx=0
WQ Output face courant=0
WQ Output face peclet=0
WQ Output face adv mass=0
WQ Output face disp mass=0
WQ Output cell mass=0
WQ Output cell source sink temp=0
WQ Output nsm pathways=0
WQ Output nsm derived pathways=0
WQ Output MaxMinRange=-1
WQ Daily Max Min Mean=-1
WQ Daily Range=0
WQ Daily Time=0
WQ Create Restart=0
WQ Fixed Restart=0
WQ System Summary=0
WQ Write To DSS=0
WQ Use Fixed Temperature=0
Sorting and Armoring Iterations= 10
XS Update Threshold= 0.02
Bed Roughness Predictor= 0
Hydraulics Update Threshold= 0.02
Energy Slope Method= 1
Volume Change Method= 1
Sediment Retention Method= 0
XS Weighting Method= 0
Number of US Weighted Cross Sections= 1
Number of DS Weighted Cross Sections= 1
Upstream XS Weight=0
Main XS Weight=1
Downstream XS Weight=0
Number of DS XS's Weighted with US Boundary= 1
Upstream Boundary Weight= 1
Weight of XSs Associated with US Boundary= 0
Number of US XS's Weighted with DS Boundary= 1
Downstream Boundary Weight= 0.5
Weight of XSs Associated with DS Boundary= 0.5
Percentile Method= 0
Sediment Output Level= 3
Mass or Volume Output= 0
Output Increment Type= 1
Profile and TS Output Increment= 1
XS Output Flag= 0
XS Output Increment= 10
Write Gradation File= 0
Read Gradation Hotstart= 0
Write HDF5 File= 1
Write Binary Output= 1
Write DSS Sediment File= 0
SV Curve= 0
Specific Gage Flag= 0

--- FORESTRN.f01 (steady flow) ---

Flow Title=Flow
Program Version=5.07
Number of Profiles= 6
Profile Names=01pct,10pct,04pct,02pct,0_2pct,01plus
River Rch & RM=FORESTRN,Main            ,8854
     623     330     438     528     868     921
River Rch & RM=FORESTRN,Main            ,5855
     682     363     481     578     950    1010
River Rch & RM=FORESTRN,Main            ,2044
     775     414     548     658    1080    1150
River Rch & RM=FORESTRN,Main            ,1690
     786     420     556     667    1090    1160
Boundary for River Rch & Prof#=FORESTRN,Main            , 1
Up Type= 0
Dn Type= 3
Dn Slope=0.00503
DSS Import GetInterval= 0
DSS Import GetPeak= 0
DSS Import FillOption= 0

--- FORESTRN.g01 (geometry) ---

Geom Title=Geometry
Program Version=5.07

River Reach=FORESTRN        ,Main
Reach XY= 30
     2141337.358      226223.775     2141202.809       226070.13
     2141234.927      225850.512     2141188.052      225252.421
     2141040.483      225034.539     2141044.823      224945.998
     2140908.538      224801.032     2140762.705      224107.456
     2140696.733      224017.178     2140770.518      223650.859
     2140659.407       223324.47     2140602.115      222959.886
     2140655.066      222863.532      2140711.49      222436.449
     2140583.886      222245.477     2140504.025      222233.324
     2140436.316      222004.157     2140464.094      221910.407
     2140398.047      221806.661     2140362.532      221425.164
     2140060.448      220514.574     2139630.235      219756.776
     2139040.374      219448.168     2138938.812      219317.091
     2138820.756      219280.633     2138567.979      218996.605
     2138574.923      218943.828     2138533.256      218927.161
     2138499.923      218975.772     2138446.052      218913.599

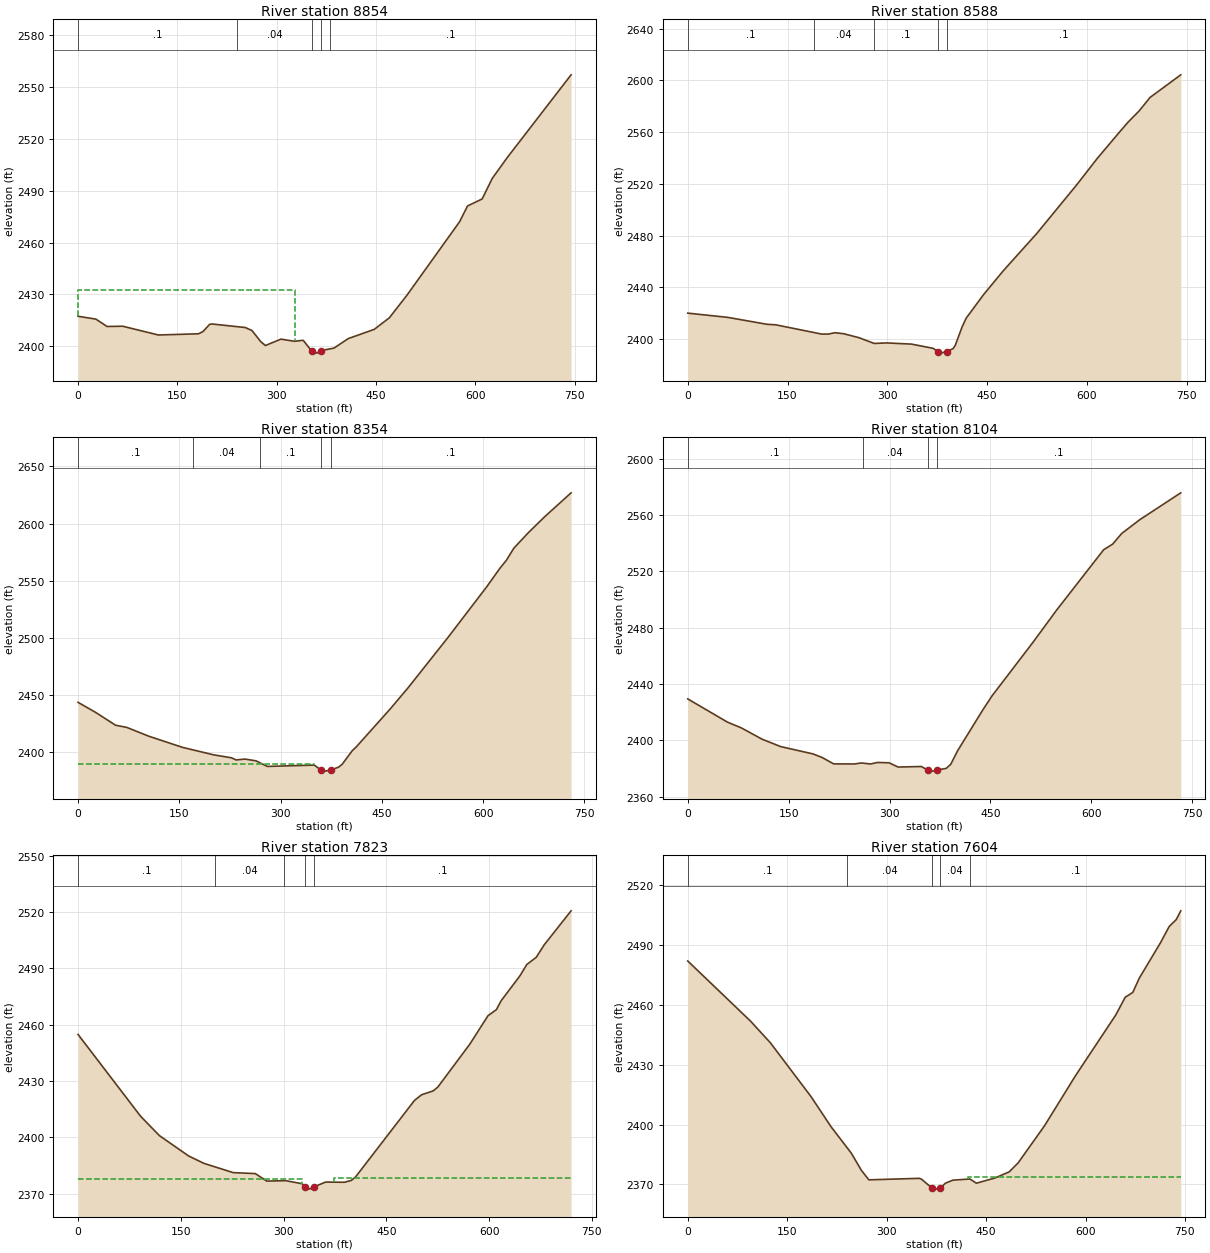
Type RM Length L Ch R = 1 ,8854    ,265.8,265.8,265.8
XS GIS Cut Line= 3
      2141686.31      226132.984     2141335.109      226214.031
     2141002.383      226406.184
#Sta/Elev= 30
       0 2417.31      27 2415.65    43.8 2411.39    67.4 2411.55   121.3 2406.47
   181.9 2407.16   188.6 2408.43   198.7 2412.62   202.1 2412.85   252.6 2410.79
   262.7 2409.04   276.1 2402.57   282.9 2400.38   306.5 2404.07   326.7 2402.84
   340.1 2403.39   352.92397.196   360.3 2395.97   366.92397.444   386.5 2398.87
   408.1 2404.38   447.4 2409.73   470.2 2416.42   496.7 2429.45   576.3 2472.03
   588.3 2481.16   610.4 2485.22   625.5 2497.03   648.2 2509.13   744.7 2557.07
#Mann= 5 ,-1 , 0
       0      .1       0     240     .04       0   352.9    .045       0
   366.9     .04       0  380.43      .1       0
#XS Ineff= 2 , 0
          328.14  2432.4
Permanent Ineff=
       F       F
Bank Sta=352.9,366.9
XS Rating Curve= 0 ,0
Exp/Cntr=0.3,0.1

Type RM Length L Ch R = 1 ,8588    ,234.8,234.2,233.2
XS GIS Cut Line= 2
     2141601.653      225986.569     2140862.721      226039.738
#Sta/Elev= 30
       0 2420.04    59.9 2416.78   119.1 2411.41   132.3 2411.01   201.3 2403.83
   211.2 2403.83   221.1 2404.88   234.2 2404.15   257.3 2401.05   280.3 2396.59
     299 2397.01   336.2 2396.09   369.1 2392.79   375.82390.177     379 2389.12
   389.12390.223   398.7 2392.61     402 2395.19   412.5 2409.71   418.4 2416.18
   444.8 2434.53   473.9 2452.65   524.5 2481.63   584.4 2519.19   615.8 2539.92
   648.5 2559.85   661.8 2567.77   678.3 2576.39   694.7  2586.8   740.8 2604.26
#Mann= 5 ,-1 , 0
       0      .1       0     190     .04       0     280      .1       0
   375.8    .045       0   389.1      .1       0
Bank Sta=375.8,389.1
XS Rating Curve= 0 ,0
Exp/Cntr=0.3,0.1

Type RM Length L Ch R = 1 ,8354    ,251.7,250,249.2
XS GIS Cut Line= 3
     2141587.207      225737.394     2141223.159       225782.22
     2140863.319      225834.667
#Sta/Elev= 30
       0 2443.54    25.8 2434.82    55.6 2423.52    72.1 2421.61   105.1 2413.84
   154.7 2404.15     201 2397.59   227.5 2394.98   234.1 2393.14   247.3  2393.9
   263.8 2392.33   280.3 2387.46   349.8 2388.63   360.22384.244   366.3 2383.35
   374.32384.286   386.2 2386.91   391.4 2389.43   406.1 2401.14   412.7 2404.89
   462.4 2437.74     489 2456.33   547.3 2499.77     605 2544.32   624.9 2560.79
   634.8 2568.05   645.6 2578.42   666.9 2591.89   691.2 2605.89   730.4 2626.86
#Mann= 5 ,-1 , 0
       0      .1       0     170     .04       0     270      .1       0
   360.2    .045       0   374.3      .1       0
#XS Ineff= 2 , 0
          349.53 2389.36
Permanent Ineff=
       F       F
Bank Sta=360.2,374.3
XS Rating Curve= 0 ,0
Exp/Cntr=0.3,0.1

Type RM Length L Ch R = 1 ,8104    ,281,281.7,280.4
XS GIS Cut Line= 3
     2141562.494      225428.428     2141214.817      225533.895
     2140851.924      225604.593
#Sta/Elev= 30
       0 2429.39    59.2 2412.86    79.8 2408.79   110.7 2400.75   138.1 2395.55
   186.1 2390.35   199.8  2387.8   216.9 2383.27   247.8  2383.2   258.1 2383.91
   271.8 2383.21   282.1 2384.27   299.2 2384.04   312.9 2381.01   347.2  2381.4
   356.8 2378.86   364.3 2378.12   370.82378.868   384.4 2380.09   391.1 2383.04
   401.1 2392.48   438.4 2421.35   452.6 2431.66   513.2 2469.52   548.2 2492.28
   618.4  2535.3   631.7 2539.25   645.1 2546.78   671.8 2556.52     733 2575.68
#Mann= 4 ,-1 , 0
       0      .1       0     260     .04       0   356.8    .045       0
   370.8      .1       0
Bank Sta=356.8,370.8
XS Rating Curve= 0 ,0
Exp/Cntr=0.3,0.1

Type RM Length L Ch R = 1 ,7823    ,220.1,218.3,214
XS GIS Cut Line= 2
     2141511.592      225163.002     2140820.403       225363.74
#Sta/Elev= 30
       0 2454.84    91.4 2411.21   118.8 2400.94   161.5 2390.08   183.7 2386.17
   226.5 2381.24   258.8 2380.71   275.4 2376.72   303.2 2376.95   327.2  2375.3
   331.82373.602   337.4 2372.44   343.72373.526   361.3 2376.21   388.6 2376.09
   398.9 2377.07   405.1 2378.95   491.1  2419.7   501.4 2422.71   518.5 2424.79
   525.3 2426.87   571.9 2449.69   598.4 2464.83   610.7 2468.08   617.5 2472.75
   644.9 2486.02   655.1 2492.13   668.8 2495.93   680.4 2502.56   719.7 2520.71
#Mann= 5 ,-1 , 0
       0      .1       0     200     .04       0     300      .1       0
   331.8    .045       0   343.7      .1       0
#XS Ineff= 2 , 0
          327.18 2377.86  374.21         2378.38
Permanent Ineff=
       F       F
Bank Sta=331.8,343.7
XS Rating Curve= 0 ,0
Exp/Cntr=0.3,0.1

Type RM Length L Ch R = 1 ,7604    ,250.4,250,248.8
XS GIS Cut Line= 3
     2141407.447      224884.786     2141081.948      225073.757
     2140793.293      225300.992
#Sta/Elev= 30
       0 2481.84    94.9 2451.68   124.5 2440.96     186 2413.96   216.3 2398.82
   246.7 2385.68   261.9 2377.08   273.2 2372.31   349.1 2373.06   352.9 2372.57
   368.92368.062   375.6 2367.66   380.82368.092   388.7 2370.64     400 2372.15
   425.7 2372.74   435.4 2370.63   463.4 2373.23   484.9  2376.3   498.5 2380.85
   538.2 2399.37   584.9 2424.42   645.7 2454.84   659.9 2463.69   671.4 2466.12
   681.1 2473.23     713  2490.9   726.3 2499.12   736.8 2502.52   743.7 2506.94
#Mann= 5 ,-1 , 0
       0      .1       0     240     .04       0   368.9    .045       0
   380.8     .04       0  426.38      .1       0
#XS Ineff= 2 , 0
                          422.22          2373.8
Permanent Ineff=
       F       F
Bank Sta=368.9,380.8
XS Rating Curve= 0 ,0
Exp/Cntr=0.3,0.1

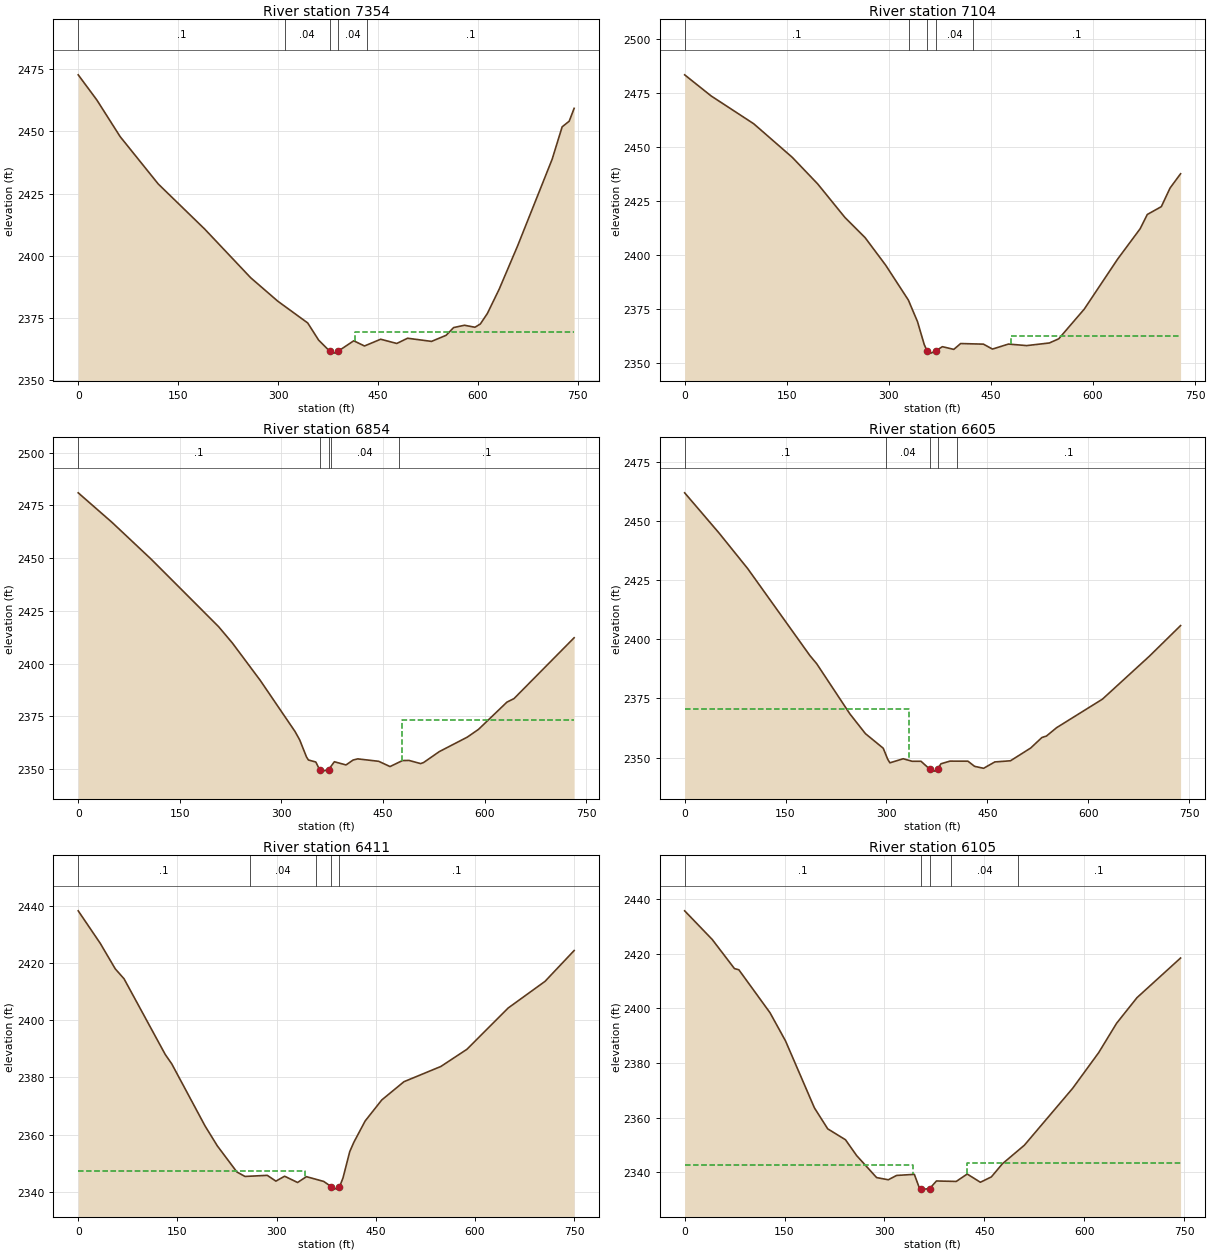
Type RM Length L Ch R = 1 ,7354    ,244.3,250,254.6
XS GIS Cut Line= 3
     2141271.058       224660.14     2140962.281      224888.306
     2140669.725      225098.919
#Sta/Elev= 30
       0 2472.65    28.1  2462.5      63 2447.82   120.1 2428.84     190 2410.68
   258.8  2391.2   299.6 2381.76   344.5 2373.02   360.8 2366.17   377.42361.732
   385.3 2360.91   390.52361.749   413.6 2365.86   429.7 2363.78     454 2366.49
   478.2 2364.79   494.4 2366.89   530.4 2365.62   552.3 2368.08   563.5 2371.17
   579.8  2372.1   595.5  2371.3   603.6 2372.61   614.1  2376.8   631.9 2386.58
   659.7 2404.07   711.4 2438.76   726.4 2451.76     737 2454.03   744.4 2459.19
#Mann= 5 ,-1 , 0
       0      .1       0     310     .04       0   377.4    .045       0
   390.5     .04       0  433.93      .1       0
#XS Ineff= 2 , 0
                          415.27         2369.53
Permanent Ineff=
       F       F
Bank Sta=377.4,390.5
XS Rating Curve= 0 ,0
Exp/Cntr=0.3,0.1

Type RM Length L Ch R = 1 ,7104    ,251.2,250,248.6
XS GIS Cut Line= 3
     2141245.568      224592.479     2140887.164      224655.728
     2140529.281      224726.422
#Sta/Elev= 30
       0 2483.34    38.9 2473.58   101.5 2460.72   158.1 2445.21   195.5 2432.91
   235.5 2417.41   265.1 2408.11   295.4 2395.35   328.7 2379.24   342.1 2369.29
   352.1 2358.62   356.42355.619     362 2354.71   368.7  2355.7   378.7 2357.69
   395.5 2356.44   405.5 2359.14     439 2358.86   452.3 2356.58   475.8  2358.9
   502.5 2358.19   535.9  2359.4   549.7 2361.34   587.2 2375.07   636.3 2398.21
   669.2 2412.16   679.8 2418.79   700.4 2422.41   713.2    2431   728.7 2437.62
#Mann= 5 ,-1 , 0
       0      .1       0     330     .04       0   356.4    .045       0
   368.7     .04       0  423.94      .1       0
#XS Ineff= 2 , 0
                          479.02         2362.66
Permanent Ineff=
       F       F
Bank Sta=356.4,368.7
XS Rating Curve= 0 ,0
Exp/Cntr=0.3,0.1

Type RM Length L Ch R = 1 ,6854    ,246.8,249.4,250.6
XS GIS Cut Line= 3
     2141179.591      224310.581     2140831.238      224413.037
     2140479.508      224524.792
#Sta/Elev= 30
       0    2481    49.8 2467.03   107.4 2449.63   207.1  2417.6   227.6 2409.79
   268.7 2392.09     320 2367.88     327 2363.85   337.1 2355.71   339.9 2354.31
   350.8 2353.35   356.62349.605   360.9 2349.03   369.6 2349.72   378.2 2353.48
   395.4 2351.96   405.8 2354.28   412.6 2354.84   443.6 2353.69   460.4  2351.2
   478.7 2354.03   488.4  2354.1   505.6  2352.6     510 2353.12   533.1 2358.28
   574.4 2365.14     591 2368.83     633 2381.75   643.4 2383.42   732.2 2412.27
#Mann= 5 ,-1 , 0
       0      .1       0   356.6    .045       0   369.6      .1       0
  373.11     .04       0  473.11      .1       0
#XS Ineff= 2 , 0
                          478.64         2373.42
Permanent Ineff=
       F       F
Bank Sta=356.6,369.6
XS Rating Curve= 0 ,0
Exp/Cntr=0.3,0.1

Type RM Length L Ch R = 1 ,6605    ,191.5,193.5,194.7
XS GIS Cut Line= 3
     2141126.585      224136.151     2140753.812      224178.887
     2140397.417      224243.423
#Sta/Elev= 30
       0 2461.96    50.9 2445.04    93.8 2429.89   186.3  2393.1   196.2 2389.74
   245.7 2368.46   268.8 2360.11   295.3 2353.93   301.9  2349.3   305.2 2347.78
     325 2349.49   338.2 2348.43   351.4 2348.43   364.22345.155   371.2 2344.26
   376.22345.268   381.2 2347.38   394.5 2348.49   421.2 2348.46   431.2 2346.27
   444.5 2345.46   461.2 2348.15   484.5 2348.64   514.5 2354.03   531.2 2358.48
   537.9 2359.09   553.1 2362.64   621.2  2374.7   691.1 2392.89   737.4 2405.82
#Mann= 5 ,-1 , 0
       0      .1       0     300     .04       0   364.2    .045       0
   376.2     .04       0  405.21      .1       0
#XS Ineff= 2 , 0
          333.56 2370.62
Permanent Ineff=
       F       F
Bank Sta=364.2,376.2
XS Rating Curve= 0 ,0
Exp/Cntr=0.3,0.1

Type RM Length L Ch R = 1 ,6411    ,303,306.1,306.3
XS GIS Cut Line= 2
     2141086.245      224006.318     2140336.462      224011.743
#Sta/Elev= 30
       0 2438.22    33.2  2426.9    56.1 2417.91    69.3 2414.46   131.6 2387.99
   141.5 2384.68   191.9 2362.95   210.4 2356.02   239.9 2346.91   252.2 2345.34
   285.8 2345.73   298.9 2343.71   312.1 2345.42   331.7 2343.23     345 2345.27
   371.1 2343.61   382.72341.761   390.6 2340.91     3952341.646   400.4 2344.87
   410.5    2354   416.7 2357.28   433.9 2364.76     459  2372.1   492.5 2378.47
   548.3  2383.8   587.7  2389.8     650 2404.23   705.8 2413.56   749.8 2424.33
#Mann= 5 ,-1 , 0
       0      .1       0     260     .04       0     360      .1       0
   382.7    .045       0     395      .1       0
#XS Ineff= 2 , 0
          343.45 2347.26
Permanent Ineff=
       F       F
Bank Sta=382.7,395
XS Rating Curve= 0 ,0
Exp/Cntr=0.3,0.1

Type RM Length L Ch R = 1 ,6105    ,254.9,250,244.6
XS GIS Cut Line= 3
     2141120.019      223791.475     2140765.664      223725.855
     2140383.366      223684.629
#Sta/Elev= 30
       0 2435.62    41.4 2425.15    74.8 2414.51    81.4 2414.07   128.2 2398.38
   151.5 2388.08   194.9 2363.61   214.9 2355.94   241.6 2351.95   258.3 2346.18
   288.3 2338.13   305.9 2337.33   318.3 2338.91     345 2339.31   351.7 2334.88
   354.92333.987   357.9 2333.91   367.92334.073   378.2 2336.89   407.9 2336.72
   424.4 2339.43   444.2 2336.42   460.7 2338.38   477.2 2343.16   510.2 2349.94
   582.8 2370.76   621.9  2383.8   648.8 2394.53   679.4 2403.88   744.9 2418.38
#Mann= 5 ,-1 , 0
       0      .1       0   354.9    .045       0   367.9      .1       0
  400.38     .04       0  500.38      .1       0
#XS Ineff= 2 , 0
          343.45 2342.91  423.53         2343.31
Permanent Ineff=
       F       F
Bank Sta=354.9,367.9
XS Rating Curve= 0 ,0
Exp/Cntr=0.3,0.1

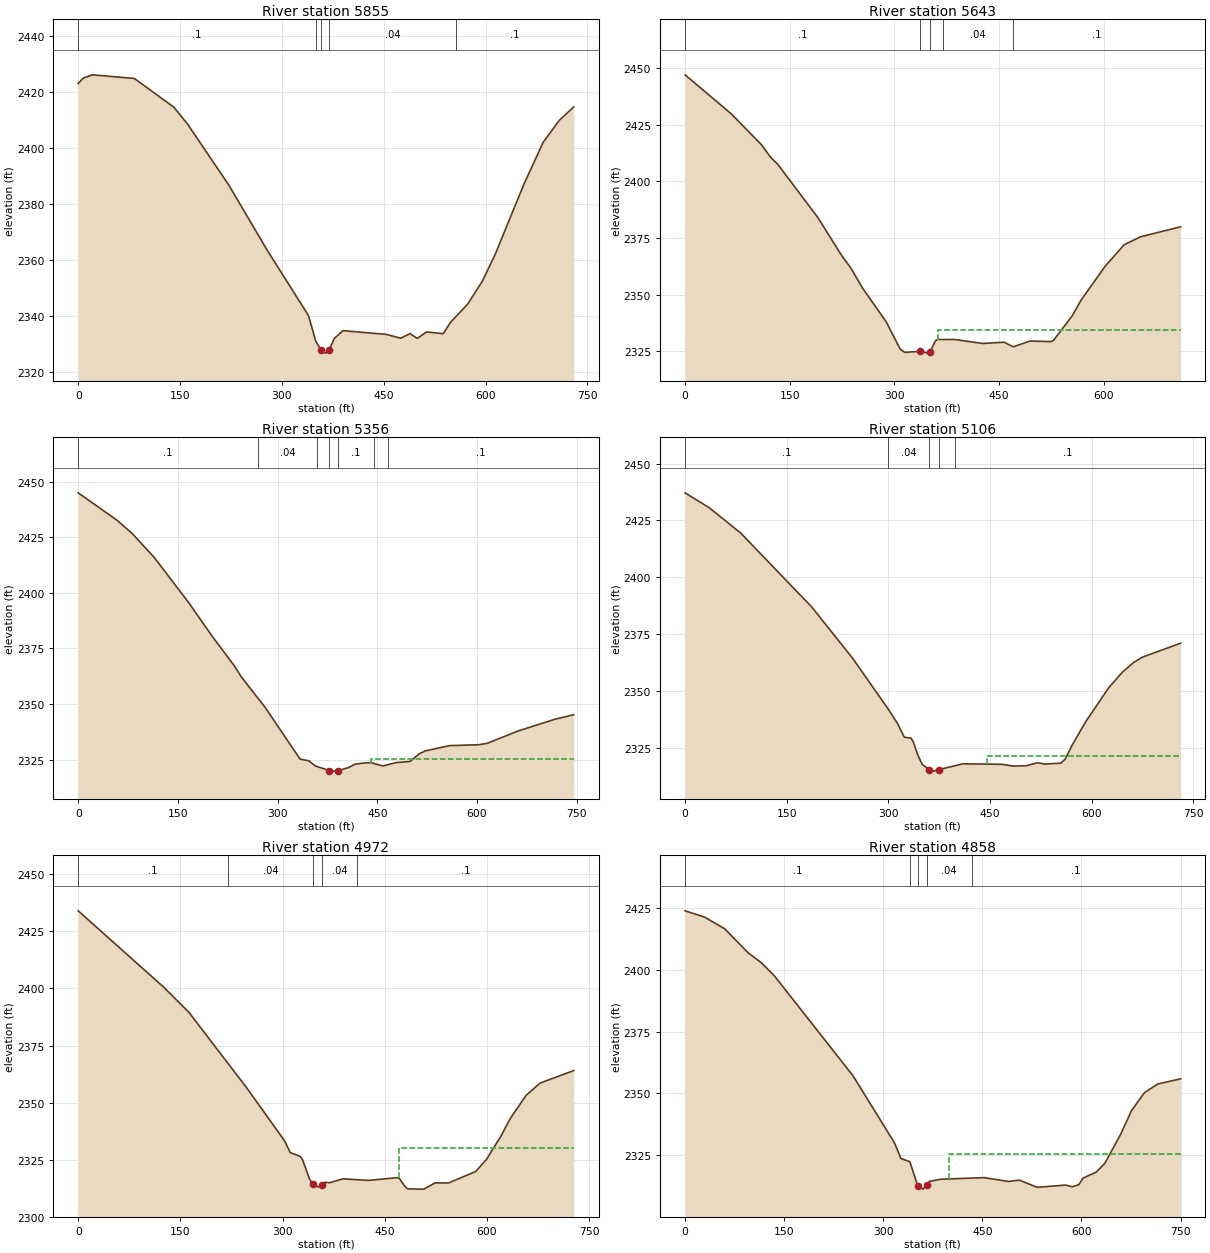
Type RM Length L Ch R = 1 ,5855    ,211,212.2,213
XS GIS Cut Line= 3
      2141063.48      223382.946     2140712.537      223487.053
     2140370.273      223610.267
#Sta/Elev= 30
       0 2423.05     7.4 2424.98    21.1 2426.16    82.7 2424.86   140.9 2414.62
     161 2408.62   221.7 2386.87   277.8 2363.82     336  2341.5   339.4  2340.1
   349.7 2331.29   357.62327.905   364.2 2326.89   369.32327.921   377.2 2332.14
   389.9  2334.9   454.1 2333.56   474.9 2332.22   488.8 2333.84   499.3 2332.17
   513.2 2334.44   537.6 2333.82   548.1 2337.81   573.8 2344.45   595.6 2352.74
   614.4 2362.29   656.5  2387.2   684.7 2402.07   708.5 2409.93   729.8 2414.75
#Mann= 5 ,-1 , 0
       0      .1       0     350     .04       0   357.6    .045       0
   369.3     .04       0  556.06      .1       0
Bank Sta=357.6,369.3
XS Rating Curve= 0 ,0
Exp/Cntr=0.3,0.1

Type RM Length L Ch R = 1 ,5643    ,282,287.2,286.9
XS GIS Cut Line= 2
     2140988.589      223204.451     2140298.484      223373.722
#Sta/Elev= 30
       0 2446.97    66.7 2429.63   109.3 2416.19   122.8 2410.53   132.9 2407.49
   190.3 2384.03   224.1 2367.43   237.6 2361.76   254.5 2352.85   288.3 2338.02
   308.6 2325.85   315.3  2324.5   337.32324.929   349.1 2324.15   351.32324.784
   359.3 2329.74   362.6 2330.17   386.8 2330.17   426.8 2328.41   457.3 2328.97
   470.7 2326.93   494.4 2329.48   525.1 2329.25   528.2 2329.73   555.2 2340.64
   567.7 2347.47   602.5 2362.55   629.5 2371.96   653.1 2375.49   710.6  2379.9
#Mann= 5 ,-1 , 0
       0      .1       0   337.3    .045       0   351.3      .1       0
     370     .04       0     470      .1       0
#XS Ineff= 2 , 0
                          362.44         2334.19
Permanent Ineff=
       F       F
Bank Sta=337.3,351.3
XS Rating Curve= 0 ,0
Exp/Cntr=0.3,0.1

Type RM Length L Ch R = 1 ,5356    ,247.5,250,253.3
XS GIS Cut Line= 3
     2140993.197      223017.667     2140607.846      223027.434
     2140252.044      223083.617
#Sta/Elev= 30
       0 2444.92    58.3 2432.62    81.2 2426.65   114.1 2415.98   166.6 2395.42
   201.3 2380.56   235.5 2366.91   245.3 2362.23   281.4 2348.41   333.9 2325.17
   347.1 2324.42   356.9 2322.09     3782320.032   386.5 2319.78   390.92320.027
   406.4 2321.32   416.4 2322.87   426.3 2323.31   439.6 2323.64   458.5 2322.12
   478.6 2323.63   499.4 2324.13   512.7 2327.47   522.6 2328.92   558.9 2331.25
   602.9 2331.65   615.6 2332.29   662.6 2337.91   718.6 2343.21   745.7 2345.14
#Mann= 7 ,-1 , 0
       0      .1       0     270     .04       0     360      .1       0
     378    .045       0   390.9      .1       0  445.47     .04       0
  465.47      .1       0
#XS Ineff= 2 , 0
                           439.9         2325.43
Permanent Ineff=
       F       F
Bank Sta=378,390.9
XS Rating Curve= 0 ,0
Exp/Cntr=0.3,0.1

Type RM Length L Ch R = 1 ,5106    ,134.4,134.1,133.1
XS GIS Cut Line= 3
     2141019.626      222841.383     2140654.461      222793.918
     2140299.499      222716.755
#Sta/Elev= 30
       0 2437.12    35.8 2430.55    82.1 2419.45   187.2 2386.89   247.5 2364.35
   300.4 2341.88   313.7  2335.7   323.6 2329.73   333.6 2329.35   336.8 2327.72
   343.4 2321.99   350.1 2317.78   360.72315.498   366.6 2314.83   374.8 2315.52
   410.2 2318.04   467.3 2317.83   484.5 2317.06   503.8  2317.2   520.3 2318.51
   531.1 2317.94   554.6 2318.33   561.3 2320.19   571.4 2326.27   591.5  2336.6
     625 2351.32   645.2 2358.23     662 2362.54   674.8 2364.89   731.5 2371.04
#Mann= 5 ,-1 , 0
       0      .1       0     300     .04       0   360.7    .045       0
   374.8     .04       0  398.24      .1       0
#XS Ineff= 2 , 0
                           445.3         2321.41
Permanent Ineff=
       F       F
Bank Sta=360.7,374.8
XS Rating Curve= 0 ,0
Exp/Cntr=0.3,0.1

Type RM Length L Ch R = 1 ,4972    ,113.1,113.3,113.5
XS GIS Cut Line= 3
2141039.23798963 222702.975664862140470.23283537222640.332895584
2140318.84614296222674.264395609
#Sta/Elev= 30
       0 2434.01   125.6 2400.54   162.7  2389.5   246.8  2356.7     303 2333.26
   311.3 2328.11   326.1 2326.37   329.4 2324.98   339.3 2316.74   344.4 2314.21
   352.5    2313   357.6 2314.07   362.4 2315.09     369 2314.87   388.9 2316.58
     426 2315.89     468 2317.09   471.3  2316.8   481.2 2312.71   484.5 2312.17
   507.5 2312.07   524.1 2314.81   543.9 2314.77   583.7 2319.81   599.3 2325.03
   620.6 2335.26   634.3 2342.98   657.7 2353.18   678.2 2358.54   727.6 2364.02
#Mann= 5 ,-1 , 0
       0      .1       0     220     .04       0   344.4    .045       0
   357.6     .04       0     410      .1       0
#XS Ineff= 2 , 0
                          470.81          2330.2
Permanent Ineff=
       F       F
Bank Sta=344.4,357.6
XS Rating Curve= 0 ,0
Exp/Cntr(USF)=0,0
Exp/Cntr=0.3,0.1

Type RM Length L Ch R = 1 ,4858    ,258.9,250.9,243.1
XS GIS Cut Line= 3
     2141062.544      222596.744     2140661.983      222546.899
     2140320.266      222604.627
#Sta/Elev= 30
       0 2423.81    29.4  2421.3    60.1 2416.53    95.4 2406.86   115.4 2402.87
   135.2 2397.54   254.2 2357.17     317 2330.05   326.9 2323.71   340.2 2322.46
     3522312.813     360 2311.35   365.82312.959   369.9 2314.48   386.4 2315.34
   452.9    2316   489.5 2314.44   506.1 2314.99     533 2312.08     576 2312.99
     586 2312.31     596 2313.14   602.6 2315.82   622.6 2318.26   635.5 2321.81
   659.2  2333.4   675.8 2343.04   695.2 2350.27   715.2  2353.8   750.2 2355.93
#Mann= 5 ,-1 , 0
       0      .1       0     340     .04       0     352    .045       0
   365.8     .04       0  433.65      .1       0
#XS Ineff= 2 , 0
                          399.24         2325.74
Permanent Ineff=
       F       F
Bank Sta=352,365.8
XS Rating Curve= 0 ,0
Exp/Cntr=0.3,0.1

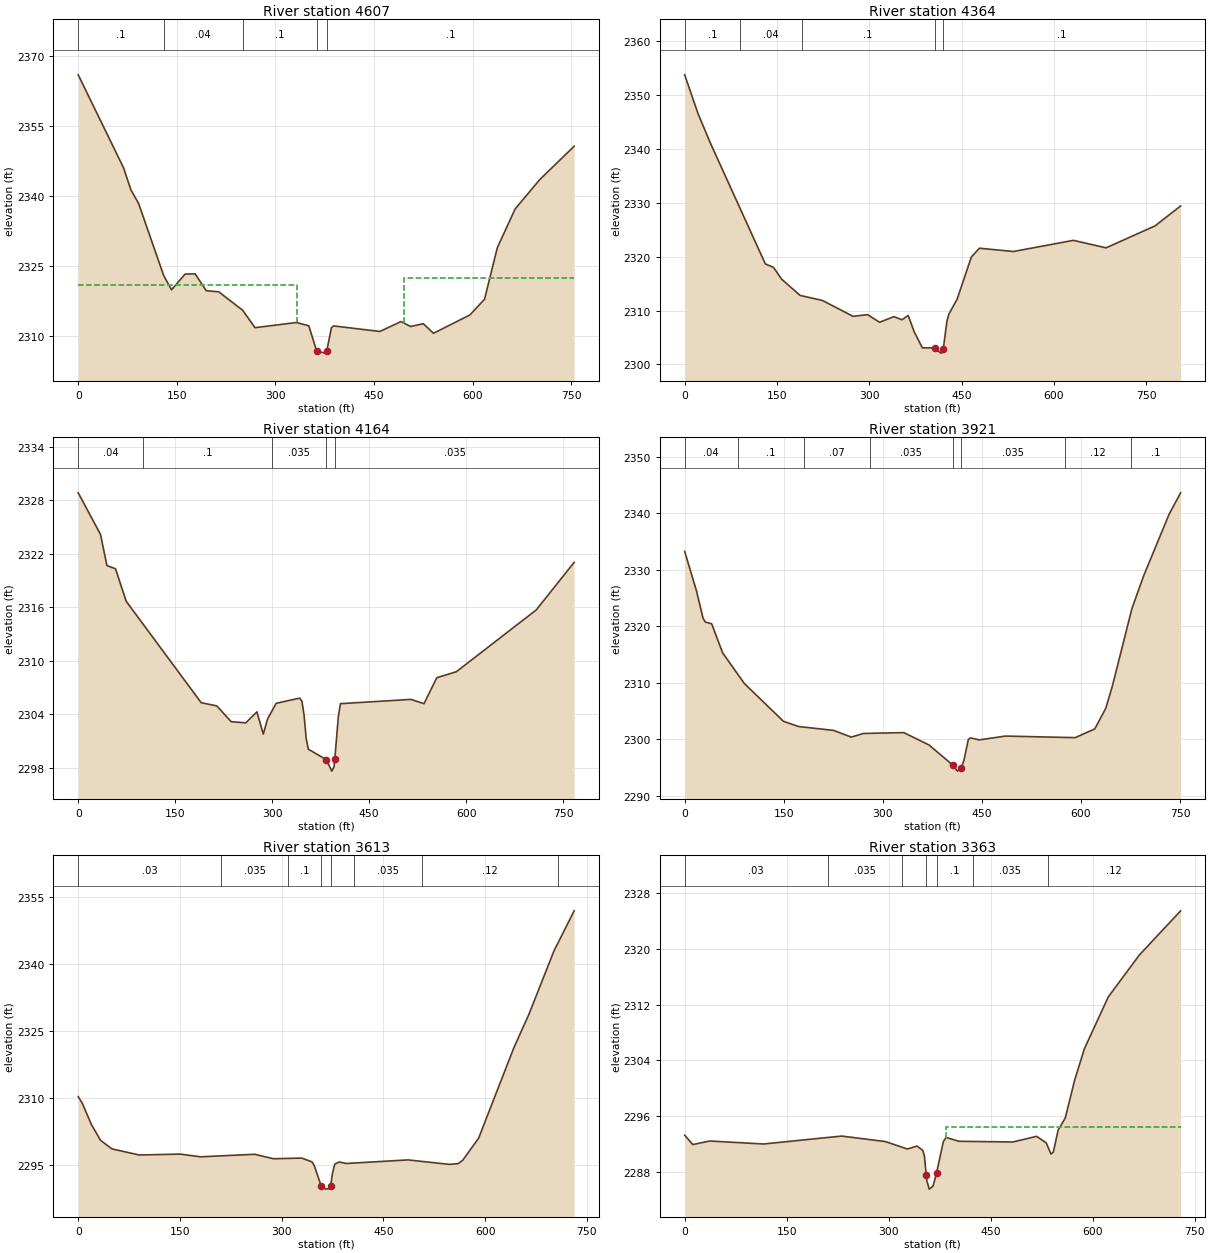
Type RM Length L Ch R = 1 ,4607    ,235.9,243.9,246.2
XS GIS Cut Line= 3
     2140941.823      222148.269      2140616.07      222340.278
        2140298.      222540.952
#Sta/Elev= 30
       0 2365.89    68.9 2345.99    80.3  2341.2    91.8 2338.36     130 2322.91
   141.9 2319.85   162.5 2323.22   177.9 2323.27   194.6 2319.67   213.8 2319.42
     250 2315.49   268.9 2311.75   331.7 2312.85   350.7 2312.15   362.8 2306.67
   376.8  2306.3  377.79 2306.68   385.1 2311.74   388.1 2312.13   458.8 2310.94
   490.9 2313.06   505.4    2312   524.8  2312.6   540.3 2310.55   595.6 2314.47
   617.9 2317.83   637.3 2328.84   664.4 2337.16   701.7 2343.43   754.2  2350.6
#Mann= 5 ,-1 , 0
       0      .1       0     130     .04       0     250      .1       0
   362.8    .045       0  377.79      .1       0
#XS Ineff= 2 , 0
           332.2 2320.84  494.92         2322.34
Permanent Ineff=
       F       F
Bank Sta=362.8,377.79
XS Rating Curve= 0 ,0
Exp/Cntr=0.3,0.1

Type RM Length L Ch R = 1 ,4364    ,200.8,200,199.6
XS GIS Cut Line= 2
     2140910.464      222118.297     2140112.938      222235.484
#Sta/Elev= 30
       0 2353.74    21.7 2346.54    41.6 2341.12   131.1 2318.65   144.4    2318
   157.6 2315.81   187.6  2312.8     224 2311.86   273.7 2308.92   297.3 2309.23
   316.8 2307.82     340 2308.86   353.3 2308.28   363.2 2309.09   373.2 2306.02
   386.4 2303.07   406.3 2303.06   416.3 2302.09   419.6 2302.22   420.4 2302.94
   426.2 2307.97   429.5 2309.34   442.8 2312.09     466 2319.94   479.1 2321.56
   534.4 2320.95   631.8 2323.02   684.9 2321.63   764.5  2325.7   806.1  2329.4
#Mann= 5 ,-1 , 0
       0      .1       0      90     .04       0     190      .1       0
   406.3    .045       0   420.4      .1       0
Bank Sta=406.3,420.4
XS Rating Curve= 0 ,0
Exp/Cntr=0.3,0.1

Type RM Length L Ch R = 1 ,4164    ,237.3,242.8,241.3
XS GIS Cut Line= 2
     2140824.743      221942.516     2140065.194      222049.938
#Sta/Elev= 30
       0 2328.81    34.5 2324.15    44.4 2320.66    57.7  2320.3    74.2 2316.66
   190.2 2305.29   214.4 2304.93   236.6 2303.16   259.1 2303.03   276.4 2304.26
   286.3 2301.77   292.9 2303.47   306.2 2305.22   342.6  2305.8     346 2305.46
   349.3 2303.94   352.6 2301.31   355.9 2300.08   383.6 2298.91   392.3 2297.62
   395.7  2298.1   396.92298.964   402.3  2303.7   405.6 2305.18   514.6 2305.66
   534.8 2305.18   554.7 2308.09   584.9 2308.76   708.4 2315.68   767.1 2321.02
#Mann= 5 ,-1 , 0
       0     .04       0     100      .1       0     300    .035       0
   383.6    .045       0   396.9    .035       0
Bank Sta=383.6,396.9
XS Rating Curve= 0 ,0
Exp/Cntr=0.3,0.1

Type RM Length L Ch R = 1 ,3921    ,307.6,307.3,305.5
XS GIS Cut Line= 3
2140808.43609673221755.1803542412140443.53009673221782.534354241
2140061.04209673221825.440354241
#Sta/Elev= 30
       0 2333.24    17.9 2326.23    27.8 2321.42    31.1 2320.74    40.9 2320.41
    57.4 2315.28    90.3 2309.84   149.5 2303.15   172.4 2302.22   225.2 2301.54
   252.2 2300.35   270.6 2300.99   331.8 2301.14   369.9 2298.95   405.72295.416
   412.9 2294.32   418.72294.915   422.8 2296.24   429.4 2299.92   432.7 2300.21
   445.9 2299.85   485.5 2300.53   591.2 2300.25   620.8 2301.79   637.4 2305.42
   647.3  2309.3   677.1 2323.12   694.9 2328.93   733.5 2339.85   750.8 2343.61
#Mann= 8 ,-1 , 0
       0     .04       0      80      .1       0     180     .07       0
     280    .035       0   405.7    .045       0   418.7    .035       0
  575.93     .12       0  675.93      .1       0
Bank Sta=405.7,418.7
XS Rating Curve= 0 ,0
Exp/Cntr=0.3,0.1

Type RM Length L Ch R = 1 ,3613    ,252.2,250,248.2
XS GIS Cut Line= 3
     2140730.975      221416.563     2140371.726      221492.259
     2140016.846      221573.466
#Sta/Elev= 30
       0 2310.42     6.1 2308.89    19.5 2304.15      33 2300.61    49.7 2298.71
    89.9 2297.34   150.3 2297.54   180.5 2296.93   260.3  2297.5   287.8  2296.5
   329.6 2296.65   344.8 2295.79   348.1 2294.93   358.2 2290.44   364.9  2289.7
     371 2289.86  372.27 2290.47     375 2293.32   378.3 2295.32   385.1 2295.78
   395.2 2295.44   486.3 2296.24   547.1 2295.24   560.1  2295.4   566.8 2296.14
   590.4 2301.11   642.2  2321.3   664.4 2328.78   701.4    2343   731.2 2351.99
#Mann= 8 ,-1 , 0
       0     .03       0     210    .035       0     310      .1       0
   358.2    .045       0  372.27      .1       0  407.14    .035       0
  507.14     .12       0  707.14      .1       0
Bank Sta=358.2,372.27
XS Rating Curve= 0 ,0
Exp/Cntr=0.3,0.1

Type RM Length L Ch R = 1 ,3363    ,247.6,250,250.9
XS GIS Cut Line= 3
     2140627.601       221114.16     2140294.685      221260.742
     2139952.892      221390.009
#Sta/Elev= 30
       0 2293.23    11.9 2291.88      37 2292.39   115.9 2291.96   230.8  2293.1
   295.1 2292.31   327.4 2291.24   341.7 2291.66   350.1 2291.04   352.5 2290.24
   355.1 2287.56     356 2286.69   359.6 2285.47   365.1  2285.9   370.32287.775
   380.3  2292.3   384.3 2292.91   403.2 2292.35   482.5 2292.25   517.6 2293.06
   531.6 2292.12   538.6 2290.51   542.1 2290.82   549.1 2293.96   559.6  2295.7
   573.5 2301.18   587.7 2305.65   622.8  2313.1   668.4 2319.12   729.2 2325.49
#Mann= 7 ,-1 , 0
       0     .03       0     210    .035       0     320      .1       0
   355.1    .045       0   370.3      .1       0  423.76    .035       0
  533.76     .12       0
#XS Ineff= 2 , 0
                           383.9         2294.44
Permanent Ineff=
       F       F
Bank Sta=355.1,370.3
XS Rating Curve= 0 ,0
Exp/Cntr=0.3,0.1

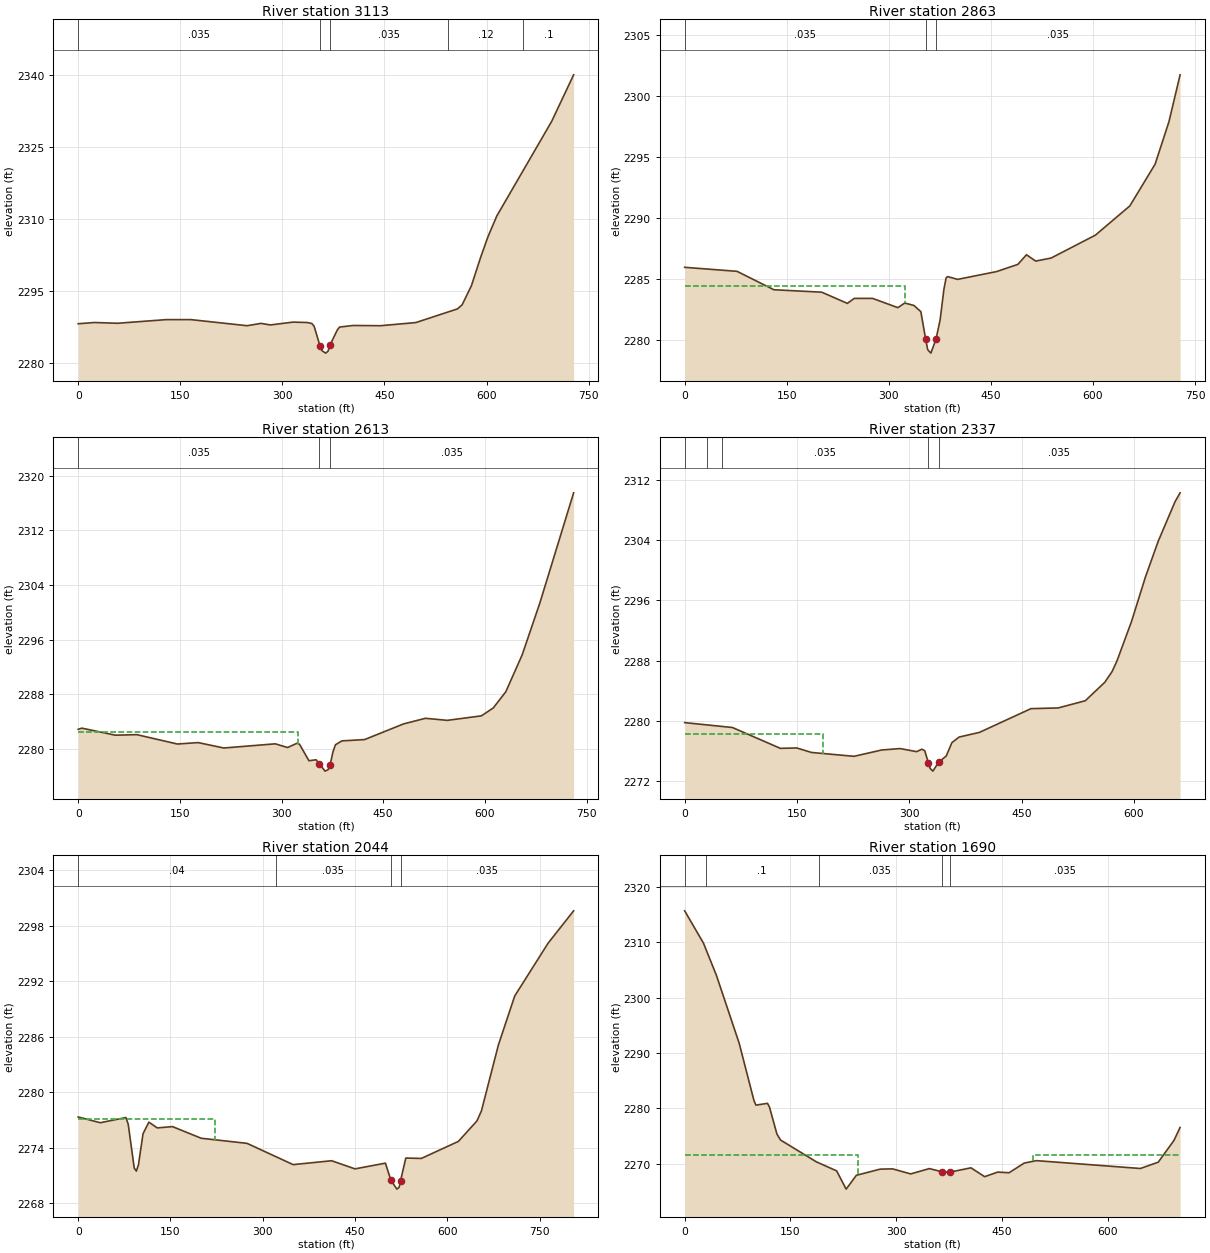
Type RM Length L Ch R = 1 ,3113    ,249.6,250,250.2
XS GIS Cut Line= 3
     2140567.648      220932.097     2140216.164      221026.727
      2139864.68      221121.358
#Sta/Elev= 30
       0 2288.13    23.9 2288.39    57.9 2288.23   129.3 2288.99   165.7 2288.99
   248.2 2287.72   268.6 2288.21   282.2 2287.88   315.6 2288.47   336.5 2288.39
   343.3 2288.19   346.7 2287.61   355.22283.568   358.4 2282.49   363.6 2282.01
   367.1  2282.4   370.12283.713   380.7 2286.82   384.1 2287.44   403.9 2287.77
   444.1 2287.72   496.2 2288.38   557.4 2291.23   564.2 2292.08   577.8 2296.05
   591.3 2301.94     602 2306.21   615.1 2310.58   695.7 2330.28     728 2339.99
#Mann= 5 ,-1 , 0
       0    .035       0   355.2    .045       0   370.1    .035       0
     544     .12       0     654      .1       0
Bank Sta=355.2,370.1
XS Rating Curve= 0 ,0
Exp/Cntr=0.3,0.1

Type RM Length L Ch R = 1 ,2863    ,251.8,250,247.7
XS GIS Cut Line= 3
     2140501.322      220701.077     2140147.484      220786.488
     2139793.647      220871.898
#Sta/Elev= 30
       0 2285.98      77 2285.65   131.1 2284.14   201.4 2283.94   239.1 2283.02
   249.2 2283.43   276.2 2283.43   313.3 2282.67   323.4 2283.05   336.9 2282.85
   347.1 2282.34   354.22280.064   357.2 2279.22   361.8 2278.94   369.42280.098
   375.4 2281.67     381 2284.19   384.2 2285.11   386.3 2285.22   401.1 2284.99
   458.4 2285.63   489.6 2286.22   502.3 2287.01   515.8 2286.49   538.5 2286.74
   603.6 2288.62   654.2 2291.02   691.3 2294.44   711.6 2297.92     728 2301.77
#Mann= 3 ,-1 , 0
       0    .035       0   354.2    .045       0   369.4    .035       0
#XS Ineff= 2 , 0
          324.46 2284.48
Permanent Ineff=
       F       F
Bank Sta=354.2,369.4
XS Rating Curve= 0 ,0
Exp/Cntr=0.3,0.1

Type RM Length L Ch R = 1 ,2613    ,276.2,276.1,275.1
XS GIS Cut Line= 3
      2140411.87      220415.319     2140073.654      220548.188
     2139737.877      220697.599
#Sta/Elev= 30
       0 2282.91     5.5 2283.08    54.9 2282.05    86.6 2282.13   146.4 2280.76
   176.9 2280.97   214.9 2280.18   290.8 2280.79   308.9 2280.25   322.8 2280.87
   326.4 2280.75   340.4 2278.32     351 2278.46   355.92277.844   364.2  2276.8
   368.7 2277.01   371.62277.713   375.9 2279.62   379.5 2280.65     389 2281.22
   422.5 2281.41     480  2283.7   512.3 2284.52   544.6 2284.22   594.9 2284.88
   612.4 2286.04   630.8 2288.39     655 2293.79   681.1 2301.38   730.9 2317.47
#Mann= 3 ,-1 , 0
       0    .035       0   355.9    .045       0   371.6    .035       0
#XS Ineff= 2 , 0
          324.46  2282.5
Permanent Ineff=
       F       F
Bank Sta=355.9,371.6
XS Rating Curve= 0 ,0
Exp/Cntr=0.3,0.1

Type RM Length L Ch R = 1 ,2337    ,291.9,293.7,293.2
XS GIS Cut Line= 2
     2140263.024      220161.483     2139665.802      220446.205
#Sta/Elev= 30
       0 2279.74    63.8 2279.09   127.8 2276.32   149.7 2276.37   169.6 2275.77
   226.2 2275.26   263.1  2276.1   287.8 2276.29   309.7 2275.88   316.9 2276.21
   320.6    2276   325.42274.426   327.8 2273.65   331.5 2273.29     3392274.457
   349.3  2275.3   356.9 2277.08   366.5 2277.82   393.6 2278.44   462.5  2281.6
   498.7 2281.69     535 2282.65     561  2285.1   570.8 2286.53   577.3 2287.94
   596.8 2293.21   615.4 2299.13   632.3 2303.84   654.9 2309.13   661.6  2310.3
#Mann= 5 ,-1 , 0
       0    .035       0      30     .04       0      50    .035       0
   325.4    .045       0     339    .035       0
#XS Ineff= 2 , 0
          184.93 2278.21
Permanent Ineff=
       F       F
Bank Sta=325.4,339
XS Rating Curve= 0 ,0
Exp/Cntr=0.3,0.1

Type RM Length L Ch R = 1 ,2044    ,358.8,353.6,349.1
XS GIS Cut Line= 3
     2140172.747      219770.858     2140132.816      219916.691
     2139539.066      220190.997
#Sta/Elev= 30
       0  2277.3      36 2276.68    77.5 2277.24    81.3 2276.53    91.1 2271.78
    94.5 2271.45    97.9 2272.11   105.4 2275.49   114.9 2276.74   128.5 2276.12
   153.3 2276.26     200    2275   274.4 2274.45   349.4 2272.15     412 2272.57
   449.9 2271.69   499.4 2272.31   508.42270.441   518.1  2269.5   521.7  2269.7
     524 2270.41   532.5 2272.86   557.8 2272.82     618 2274.66   648.2 2276.88
   655.4 2277.95     683 2285.08   709.6 2290.39   763.8 2296.09   805.3 2299.59
#Mann= 4 ,-1 , 0
       0     .04       0   321.2    .035       0   508.4    .045       0
     524    .035       0
#XS Ineff= 2 , 0
          221.88 2277.06
Permanent Ineff=
       F       F
Bank Sta=508.4,524
XS Rating Curve= 0 ,0
Exp/Cntr=0.3,0.1

Type RM Length L Ch R = 1 ,1690    ,317.4,318.7,315.2
XS GIS Cut Line= 2
     2139865.455       219470.51     2139424.483      220017.385
#Sta/Elev= 30
       0 2315.68    26.7 2309.84    45.1    2304    77.3 2291.76    98.3 2281.39
   101.1 2280.57   117.5 2280.89   120.3 2280.21   130.8 2275.36     136 2274.26
   186.8 2270.32   215.5 2268.69     229 2265.39   243.5 2267.89   277.1    2269
   294.8 2269.05   320.5 2268.14     347  2269.1   365.22268.514   375.82268.456
     406 2269.24   425.4 2267.64   443.9 2268.47     460 2268.35   481.4 2270.09
   498.7 2270.54   646.2 2269.12   671.5 2270.26   693.8 2274.19   702.5 2276.53
#Mann= 5 ,-1 , 0
       0     .04       0      30      .1       0     190    .035       0
   365.2    .045       0   375.8    .035       0
#XS Ineff= 2 , 0
          246.32 2271.59  493.68         2271.47
Permanent Ineff=
       F       F
Bank Sta=365.2,375.8
XS Rating Curve= 0 ,0
Exp/Cntr=0.3,0.1