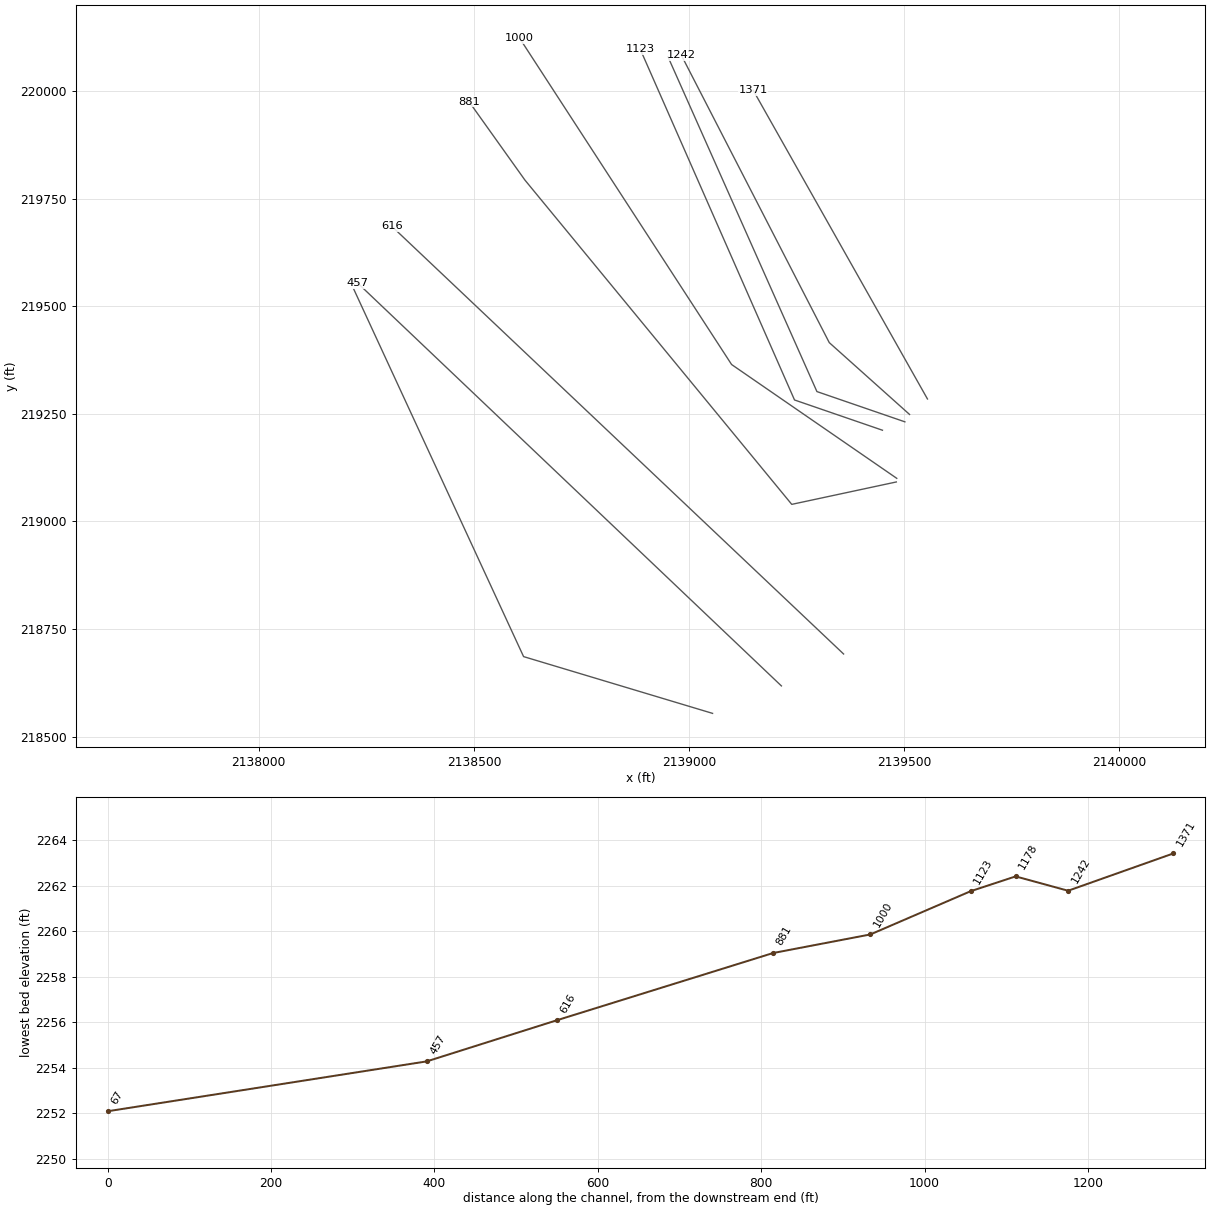
HEC-RAS study FORESTRN.prj: FORESTRN

--- FORESTRN.g01 (geometry) --- (continued)

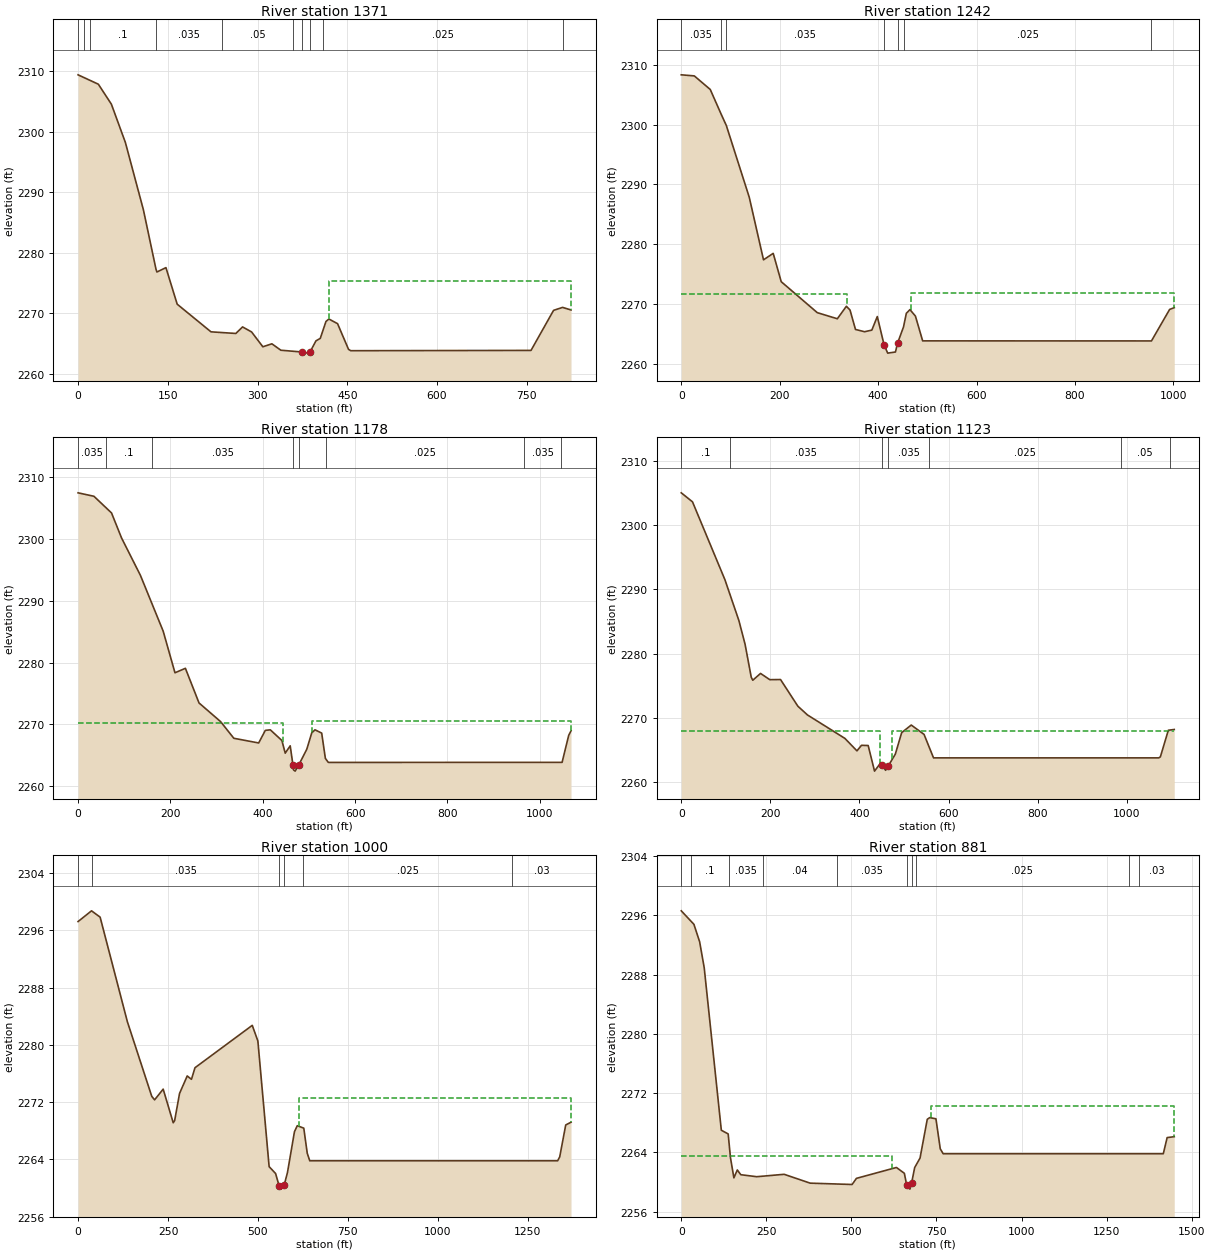
Type RM Length L Ch R = 1 ,1371    ,129.8,129,128.8
XS GIS Cut Line= 2
2139554.17762214219284.6205185392139149.03521483 220002.29811832
#Sta/Elev= 30
       0 2309.42    33.9 2307.87    55.7 2304.57    79.1 2298.24   109.2 2287.12
   130.3 2277.28   131.8 2276.83   146.9 2277.55   165.7 2271.51   222.2 2266.94
   263.7 2266.67     275 2267.75   290.1 2266.92   308.9 2264.47     324 2264.96
     339  2263.9   374.62263.605   384.2 2263.42   387.92263.624   397.6 2265.44
   404.9 2265.86   414.4 2268.65   419.3 2269.06   433.8 2268.29   452.1 2264.05
   455.8 2263.82   757.2 2263.87   794.9 2270.49     810 2270.98   824.1 2270.55
#Mann= 10 ,-1 , 0
       0     .04       0      10    .035       0      20      .1       0
     130    .035       0     240     .05       0     360    .035       0
   374.6    .045       0   387.9    .035       0     410    .025       0
     810    .035       0
#XS Ineff= 2 , 0
                          419.93         2275.34
Permanent Ineff=
       F       F
Bank Sta=374.6,387.9
XS Rating Curve= 0 ,0
Exp/Cntr=0.3,0.1

Type RM Length L Ch R = 1 ,1242    ,64.4,64.2,63.1
XS GIS Cut Line= 3
2139512.58971943219248.6149366742139325.95680122219415.602284547
 2138982.1593203220083.551676037
#Sta/Elev= 30
       0 2308.34    26.5 2308.16    58.9 2305.89      80 2301.95    91.6 2299.85
   138.1 2287.87   167.1 2277.39   186.8 2278.47   203.1 2273.73   276.4 2268.55
   317.1 2267.53   335.5 2269.62   342.9 2268.99     354 2265.74   372.4 2265.36
   387.2 2265.63   398.3  2267.9   412.3 2263.09   419.5 2261.78   435.2 2261.97
   439.6 2263.48   451.8 2266.21   451.8 2266.25   457.3 2268.44   464.7 2269.06
   475.8 2267.97   490.5 2263.83   955.4 2263.82   992.3 2269.09  1001.7 2269.39
#Mann= 7 ,-1 , 0
       0    .035       0      80      .1       0    91.6    .035       0
   412.3    .045       0   439.6    .035       0   451.8    .025       0
   955.4    .035       0
#XS Ineff= 2 , 0
          335.76 2271.73  465.79         2271.77
Permanent Ineff=
       F       F
Bank Sta=412.3,439.6
XS Rating Curve= 0 ,0
Exp/Cntr(USF)=0,0
Exp/Cntr=0.5,0.3

Type RM Length L Ch R = 1 ,1178    ,56,55.1,55.3
XS GIS Cut Line= 3
     2139501.696      219231.491     2139297.269      219301.804
2138951.08566685220079.925629224
#Sta/Elev= 30
       0 2307.48    34.4 2306.92    72.5 2304.22    94.2 2300.17   135.1 2294.11
   184.4 2285.07   209.9 2278.34   232.5 2279.06     262 2273.45   308.7 2270.43
   337.4 2267.73   391.2 2266.97   405.6 2269.01   416.4  2269.1   441.5 2267.37
   448.7 2265.32   459.5 2266.51   465.52263.375   466.6 2262.62   470.2 2262.41
   477.82263.372   495.4 2265.95   506.1 2268.59   513.2  2269.1   527.7 2268.57
   535.7 2264.47   542.1 2263.82  1048.4 2263.83  1062.7 2268.19  1067.8 2268.95
#Mann= 8 ,-1 , 0
       0    .035       0      60      .1       0     160    .035       0
   465.5    .045       0   477.8    .035       0  536.18    .025       0
  966.18    .035       0 1046.18     .05       0
#XS Ineff= 2 , 0
          443.39 2270.28  506.44         2270.53
Permanent Ineff=
       F       F
Bank Sta=465.5,477.8
XS Rating Curve= 0 ,0
Exp/Cntr=0.5,0.3

Type RM Length L Ch R = 1 ,1123    ,119,122.8,123.7
XS GIS Cut Line= 3
     2139449.613       219211.96     2139245.186      219282.273
2138886.72418539220097.230073608
#Sta/Elev= 30
       0    2305    25.2  2303.6    98.1 2291.48   129.3 2285.16   143.2 2281.48
   157.1 2276.34   160.5 2275.88   177.9 2276.94   198.7 2275.97   222.8 2275.99
   261.7 2271.85   283.2 2270.49   367.2 2266.85   394.3 2264.91   404.5 2265.77
   419.5 2265.74   433.8 2261.76   448.1 2263.09   450.12262.662   458.8 2261.89
   464.92262.608   480.4 2264.39   494.7 2267.74   516.2 2268.92   544.9 2267.47
   566.2 2263.82  1071.7 2263.82  1075.3 2263.97  1093.2 2268.11  1106.5 2268.23
#Mann= 7 ,-1 , 0
       0      .1       0     110    .035       0   450.1    .045       0
   464.9    .035       0  556.18    .025       0  986.18     .05       0
 1096.18    .035       0
#XS Ineff= 2 , 0
           446.7    2268   473.3            2268
Permanent Ineff=
       F       F
Bank Sta=450.1,464.9
XS Rating Curve= 0 ,0
Exp/Cntr=0.5,0.3

Type RM Length L Ch R = 1 ,1000    ,115.3,119.1,119.1
XS GIS Cut Line= 3
2139482.82668037219100.143538845  2139098.927679219364.695700409
2138606.43778759220122.842816713
#Sta/Elev= 30
       0 2297.24    37.4 2298.74    61.3 2297.86     137 2283.26   204.8 2272.83
   212.7 2272.33   236.6 2273.83   264.5 2269.13   268.5 2269.44   282.1 2273.23
   303.4 2275.67   315.2  2275.2     325 2276.82   484.2 2282.74   499.8 2280.56
   531.1    2263   549.1 2262.04   558.6 2260.36   563.4 2259.86   573.32260.501
     582 2262.16   601.5 2267.88   609.3 2268.72   627.4 2268.38   637.1 2264.86
     644 2263.82  1333.1 2263.82  1338.9 2264.38  1355.5 2268.82  1370.3 2269.21
#Mann= 6 ,-1 , 0
       0      .1       0      40    .035       0   558.6    .045       0
   573.3    .035       0  626.23    .025       0 1206.23     .03       0
#XS Ineff= 2 , 0
                          615.26         2272.54
Permanent Ineff=
       F       F
Bank Sta=558.6,573.3
XS Rating Curve= 0 ,0
Exp/Cntr(USF)=0,0
Exp/Cntr=0.3,0.1

Type RM Length L Ch R = 1 ,881     ,255.7,265.1,263.4
XS GIS Cut Line= 4
     2139481.818      219091.734     2139238.762      219039.651
2138618.54695141 219793.435224672138488.45044979219975.946455441
#Sta/Elev= 30
       02296.595  37.1892294.773  53.965 2292.42  67.3872288.929 117.7162266.992
 137.8482266.493 144.5592263.292 154.6252260.567 164.6912261.629 174.9182260.991
 221.7312260.719 302.3442261.044  378.822259.851 502.0312259.669 514.7762260.497
 632.3592261.965 655.6682261.178   662.52259.595 671.9922259.044   676.72259.813
 685.9682261.952 701.7172263.235  722.96 2268.46 730.2542268.694 748.4522268.532
 761.1982264.483 769.6952263.8181416.6582263.8181427.9632265.996 1448.852266.122
#Mann= 10 ,-1 , 0
       0     .04       0      30      .1       0     140    .035       0
     240     .04       0  458.57    .035       0   662.5    .045       0
   676.7    .035       0  688.57    .025       0 1314.72      .1       0
 1344.72     .03       0
#XS Ineff= 2 , 0
          617.96 2263.51     735         2270.32
Permanent Ineff=
       F       F
Bank Sta=662.5,676.7
XS Rating Curve= 0 ,0
Exp/Cntr=0.3,0.1

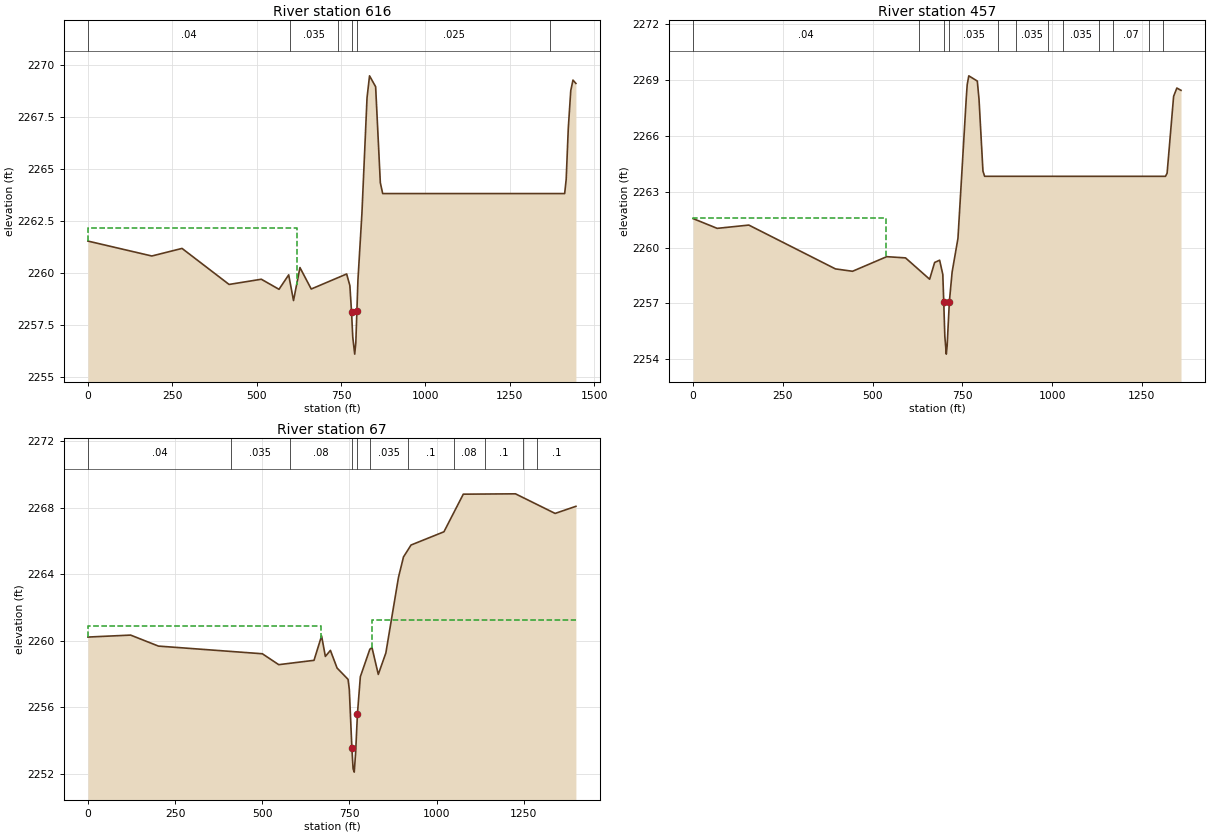
Type RM Length L Ch R = 1 ,616     ,157.3,158.9,157.7
XS GIS Cut Line= 2
     2139359.248      218691.865 2138309.0476821219686.038912147
#Sta/Elev= 30
       0 2261.53 189.2762260.812 278.8532261.177 418.3482259.442 513.7952259.693
  566.292259.208 594.9242259.904 609.2412258.667  628.332260.255 661.7372259.222
 766.7282259.946 776.2732259.385   781.32258.094 784.8392256.906  790.592256.087
 793.8752256.634   797.12258.182 800.1342259.639 811.9462262.853 827.0892268.422
 834.5342269.487 852.6172268.963 866.5422264.339 873.5042263.8181412.8042263.818
1417.3222264.4981423.5272266.9511430.8752268.7721437.4512269.2821446.1342269.121
#Mann= 6 ,-1 , 0
       0     .04       0     600    .035       0     740    .025       0
   781.3    .045       0   797.1    .025       0    1370     .08       0
#XS Ineff= 2 , 0
          618.31 2262.15
Permanent Ineff=
       F       F
Bank Sta=781.3,797.1
XS Rating Curve= 0 ,0
Exp/Cntr=0.3,0.1

Type RM Length L Ch R = 1 ,457     ,390.6,390.6,390.6
XS GIS Cut Line= 2
     2139214.717      218617.6462138229.71514536219554.130448885
#Sta/Elev= 30
       02261.553  67.1922261.028 155.3772261.204 396.5542258.855 444.1692258.727
 539.399 2259.51 591.7752259.445 658.955  2258.3 672.8792259.199 686.8032259.321
 695.6642258.556   698.32257.067  701.29 2255.24 705.3682254.285 707.6892254.717
   713.92257.098 721.6132258.689 737.8572260.491 761.0632268.038 763.5692268.726
 768.0252269.206 791.7582268.925  796.522267.951 807.4762264.101 812.1172263.819
1315.8592263.8181320.3862263.9841338.4942268.1051347.5482268.5511359.1292268.428
#Mann= 12 ,-1 , 0
       0     .04       0     630    .035       0   698.3    .045       0
   713.9    .035       0     850    .025       0     900    .035       0
     990    .025       0    1030    .035       0    1130    .025       0
    1170     .07       0    1270     .08       0    1310      .1       0
#XS Ineff= 2 , 0
          537.89 2261.57
Permanent Ineff=
       F       F
Bank Sta=698.3,713.9
XS Rating Curve= 0 ,0
Exp/Cntr=0.3,0.1

Type RM Length L Ch R = 1 ,67      ,87.8,71.2,76.4
XS GIS Cut Line= 3
     2139054.691      218553.844     2138615.455      218685.788
2138220.71315974219539.883057511
#Sta/Elev= 30
       02260.219 122.3652260.338 202.1922259.676 500.2392259.215 547.2252258.559
 648.425 2258.82  670.11 2260.29 680.9532259.054 695.4112259.418 714.5352258.357
 746.0112257.676 749.6252257.076     7572253.548 760.4682252.303 763.7342252.095
 767.6962253.233     7732255.611 781.2752257.833 808.4662259.485 814.6822259.587
 832.7542257.974 854.4392259.263 890.5822263.804 905.0392265.039 926.7252265.756
1021.0452266.5521076.5412268.8141226.2092268.8351339.9152267.6561399.5292268.084
#Mann= 11 ,-1 , 0
       0     .04       0     410    .035       0  578.63     .08       0
     757    .045       0     773     .08       0  808.63    .035       0
  918.63      .1       0 1048.63     .08       0 1138.63      .1       0
 1248.63     .07       0 1288.63      .1       0
#XS Ineff= 2 , 0
          667.49 2260.88  813.42         2261.27
Permanent Ineff=
       F       F
Bank Sta=757,773
XS Rating Curve= 0 ,0
Exp/Cntr=0.3,0.1
LCMann Table=0

Chan Stop Cuts=-1
Use User Specified Reach Order=0
Composite Channel Slope=5